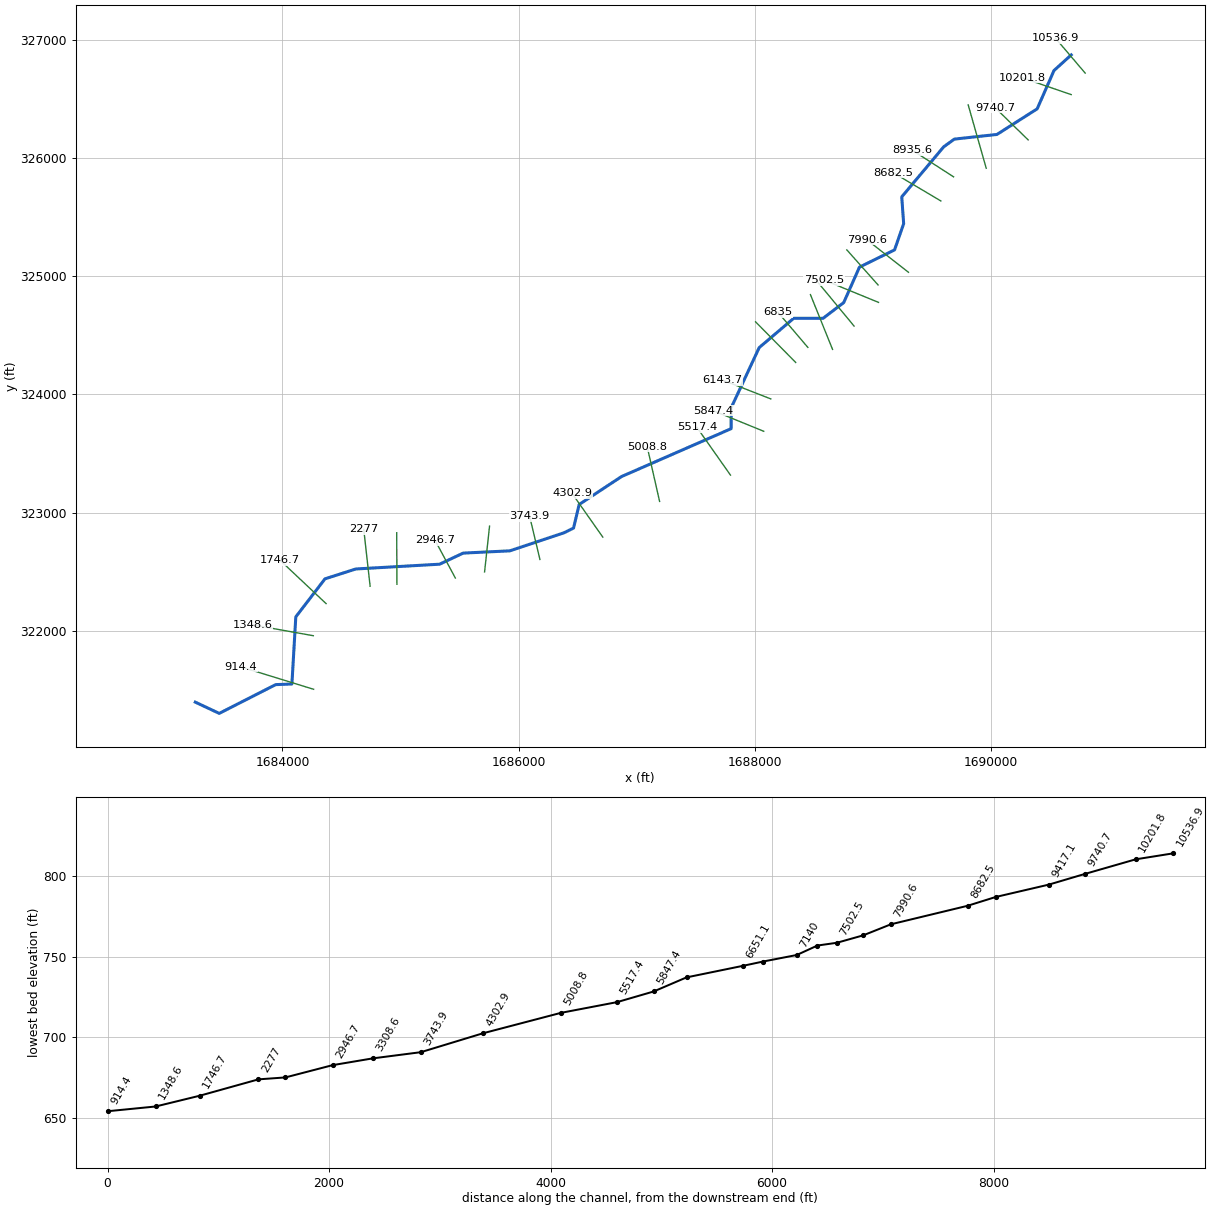
--- CROOKEDCRK.prj (project) ---

Proj Title=CROOKEDCRK
Current Plan=p01
Default Exp/Contr=0,0
English Units
Geom File=g01
Flow File=f01
Plan File=p01
BEGIN DESCRIPTION:
END DESCRIPTION:
DSS Export Rating Curves= 0
DSS Export Rating Curve Sorted= 0
DSS Export Volume Flow Curves= 0
DXF OffsetX= 0
DXF OffsetY= 0
DXF ScaleX= 0
DXF ScaleY= 0

--- CROOKEDCRK.p01 (plan) ---

Plan Title=Floodplain
Program Version=4.00
Geom File=g01
Flow File=f01
K Sum by GR=0
Std Step Tol=0.01
Critical Tol=0.01
Num of Std Step Trials=20
Max Error Tol=0.3
Flow Tol Ratio=0.001
Split Flow NTrial=30
Split Flow Tol=0.02
Split Flow Ratio=0.02
Log Output Level=0
Friction Slope Method=1
Unsteady Friction Slope Method=2
Unsteady Bridges Friction Slope Method=1
Global Log Level=0
CheckData=False
Run HTab=0
Run UNet=0
Run PostProcess=0
UNET Theta=0
UNET Theta Warmup=0
UNET ZTol=0
UNET ZSATol=0
UNET MxIter=0
UNET MaxInSteps=0
UNET DtIC=0
UNET DtMin=0
UNET MaxCRTS=0
UNET WFStab=0
UNET SFStab=0
UNET WFX=0
UNET SFX=0
UNET DSS MLevel=0
UNET DZMax Abort=0
UNET Convert EG Bridges=0
UNET Use Existing IB Tables=0
UNET Froude Limit=0
UNET Froude Power=0
Write IC File=0
Echo Input=False
Echo Output=False
Write Detailed=0

--- CROOKEDCRK.f01 (steady flow) ---

Flow Title=NFF Regression Equation
Program Version=4.00
Number of Profiles=1
Profile Names=P100yr
River Rch & RM=CROOKEDCRK,Main      ,10536.9
897.6510
River Rch & RM=CROOKEDCRK,Main      ,9740.7
909.5346
River Rch & RM=CROOKEDCRK,Main      ,7990.6
1007.708
River Rch & RM=CROOKEDCRK,Main      ,5517.4
1104.150
River Rch & RM=CROOKEDCRK,Main      ,914.4
1204.442
Boundary for River Rch & Prof#=CROOKEDCRK,Main      ,1
Up Type=0
Dn Type=3
Dn Slope=0.014976

--- CROOKEDCRK.g01 (geometry) ---

Geom Title=USGS 10m DEM
Program Version=4.10

River Reach=CROOKEDCRK      ,Main
Reach XY= 30
     1690680.319      326872.874     1690534.354      326740.811
     1690391.865      326416.445     1690051.281      326199.815
     1689691.003      326160.428     1689600.644      326095.554
        1689245.      325671.562     1689261.218      325444.506
     1689184.201      325222.897     1688887.038      325077.277
     1688753.817      324777.239     1688578.891      324644.017
     1688329.824      324644.017     1688037.895      324396.108
     1687800.413      323886.391     1687800.413      323710.306
     1686871.952      323304.948     1686513.375      323068.525
     1686465.878      322869.272     1686387.104      322829.884
     1685926.266      322676.405     1685531.009      322657.275
     1685331.756      322563.441     1684621.626      322522.895
     1684360.975      322439.487     1684113.839      322117.824
     1684080.823      321549.604     1683943.547      321544.391
      1683465.45      321301.109     1683262.764      321396.082

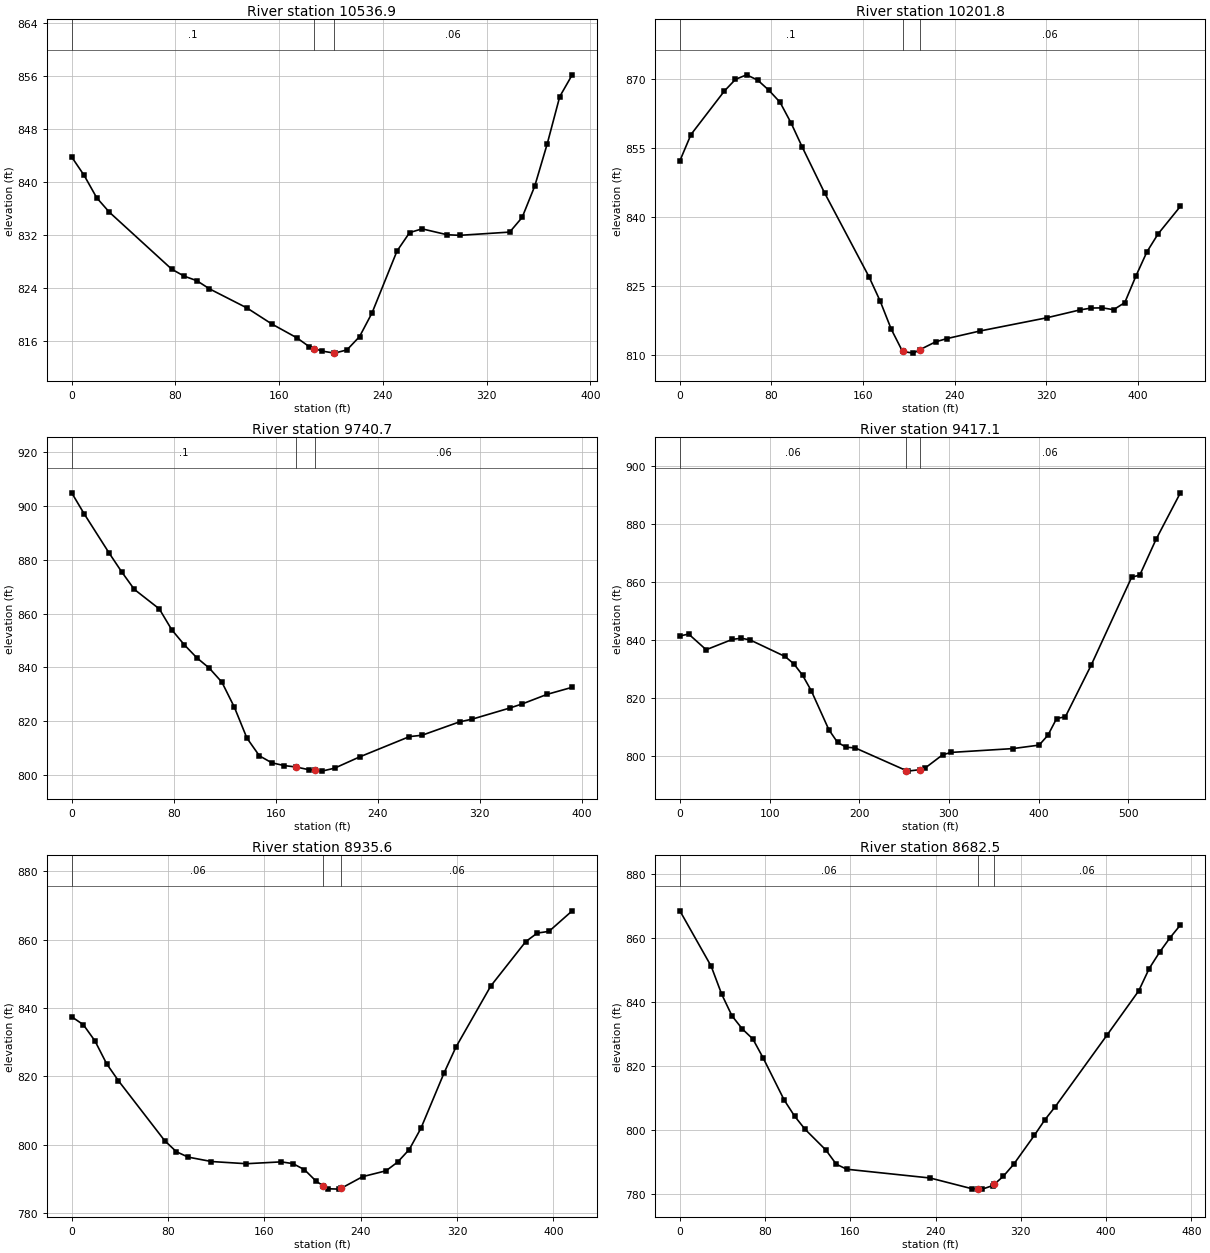
Type RM Length L Ch R = 1 ,10536.9 ,323.1,335.2,347.3
XS GIS Cut Line= 2
     1690798.149      326719.162     1690547.931      327013.099
#Sta/Elev= 30
       0   843.8     9.6  841.02    19.3  837.63      29  835.46    77.2  826.82
    86.8  825.77    96.5  825.09   106.2  823.86   135.1  820.97   154.4  818.53
   173.7  816.44   183.4  815.08   187.2  814.83     193  814.44   202.2  814.15
   202.7  814.13   212.3  814.62     222  816.63   231.6   820.2   250.9  829.58
   260.6  832.36   270.2  832.93   289.5  832.04   299.2  831.95   337.8  832.44
   347.4  834.66   357.1  839.39   366.7  845.76   376.4  852.94     386  856.23
#Mann= 3 , 0 , 0
       0      .1       0   187.2    .045       0   202.2     .06       0
Bank Sta=187.2,202.2
XS Rating Curve= 0 ,0
Exp/Cntr=0.3,0.1

Type RM Length L Ch R = 1 ,10201.8 ,471,461.2,451.4
XS GIS Cut Line= 2
     1690679.871       326537.01     1690266.195      326678.998
#Sta/Elev= 30
       0  852.18     9.7  857.88    38.9  867.32    48.6  869.85    58.3  870.83
      68  869.68    77.8  867.48    87.5  864.89    97.2  860.37   106.9  855.17
   126.4  845.24   165.2  827.06     175  821.77   184.7  815.66   194.6  810.82
   204.1  810.46   209.6  811.19   223.5  812.91   233.3  813.61   262.4  815.27
   320.7  818.13   349.9  819.85   359.6  820.24   369.3  820.28     379  819.88
   388.8  821.42   398.5  827.16   408.2  832.45   417.9  836.32   437.4   842.3
#Mann= 3 , 0 , 0
       0      .1       0   194.6    .045       0   209.6     .06       0
Bank Sta=194.6,209.6
XS Rating Curve= 0 ,0
Exp/Cntr=0.3,0.1

Type RM Length L Ch R = 1 ,9740.7  ,335.7,323.2,310.7
XS GIS Cut Line= 2
     1690315.494      326153.697      1690034.39      326427.615
#Sta/Elev= 30
       0  904.95     9.8  897.12    29.4   882.5    39.2  875.53    49.1  869.01
    68.7  861.74    78.5  853.95    88.3  848.38    98.1  843.55   107.9  839.69
   117.8  834.45   127.6  825.11   137.4  813.65   147.2  807.04     157  804.42
   166.8   803.4   175.7  802.89   186.4  801.84   190.7  801.62   196.2  801.34
   206.1  802.43   225.7  806.61   264.9   814.2   274.7  814.69   304.2  819.69
     314  820.68   343.4  824.81   353.2  826.34   372.9  829.94   392.5  832.55
#Mann= 3 , 0 , 0
       0      .1       0   175.7    .045       0   190.7     .06       0
Bank Sta=175.7,190.7
XS Rating Curve= 0 ,0
Exp/Cntr=0.3,0.1

Type RM Length L Ch R = 1 ,9417.1  ,464.9,481.3,497.8
XS GIS Cut Line= 3
     1689960.545       325913.69     1689837.409       326345.82
     1689807.632      326450.318
#Sta/Elev= 30
       0  841.35     9.8     842    29.3   836.6    58.6  840.18    68.4  840.56
    78.1     840   117.2  834.28     127  831.75   136.8  827.81   146.5  822.45
   166.1  809.02   175.8  804.64   185.6  802.98   195.4  802.76   252.6  794.91
     254  794.75   267.6  795.25   273.5  795.83     293   800.4   302.8  801.21
   371.2  802.52   400.5  803.72   410.3  807.12     420  812.87   429.8   813.5
   458.4   831.2   503.7  861.61   512.7  862.31   530.8  874.61     558  890.69
#Mann= 3 , 0 , 0
       0     .06       0   252.6    .045       0   267.6     .06       0
Bank Sta=252.6,267.6
XS Rating Curve= 0 ,0
Exp/Cntr=0.3,0.1

Type RM Length L Ch R = 1 ,8935.6  ,252,253.1,254.2
XS GIS Cut Line= 2
     1689683.859      325841.208     1689334.479      326066.357
#Sta/Elev= 30
       0  837.43     9.7   835.1    19.3  830.38      29   823.7    38.7  818.78
    77.3  801.17      87  797.96    96.7   796.4     116  795.11     145  794.47
     174  795.01   183.7   794.5   193.3  792.72     203  789.35   208.9     788
   212.6  787.15   222.3  787.04   223.9  787.31   241.6  790.69     261   792.4
   270.6  794.93   280.3  798.62     290  804.84   309.3  821.08     319  828.52
     348  846.43     377  859.39   386.6   861.9   396.3  862.39   415.6   868.4
#Mann= 3 , 0 , 0
       0     .06       0   208.9    .045       0   223.9     .06       0
Bank Sta=208.9,223.9
XS Rating Curve= 0 ,0
Exp/Cntr=0.3,0.1

Type RM Length L Ch R = 1 ,8682.5  ,694.7,691.7,688.9
XS GIS Cut Line= 2
     1689576.462       325637.04     1689172.224      325876.517
#Sta/Elev= 30
       0  868.42    29.4  851.12    39.2  842.44    48.9  835.65    58.7  831.53
    68.5  828.43    78.3  822.43    97.9  809.39   107.7  804.35   117.5  800.26
     137   793.8   146.8  789.37   156.6   787.8   234.9  785.06   274.1  781.72
     280  781.64   283.9  781.59   293.7  782.71     295  783.09   303.4  785.53
   313.2  789.28   332.8   798.4   342.6  803.23   352.4  807.35   401.3  829.82
   430.7  843.46   440.5   850.4   450.3  855.53   460.1  860.03   469.8     864
#Mann= 3 , 0 , 0
       0     .06       0     280    .045       0     295     .06       0
Bank Sta=280,295
XS Rating Curve= 0 ,0
Exp/Cntr=0.3,0.1

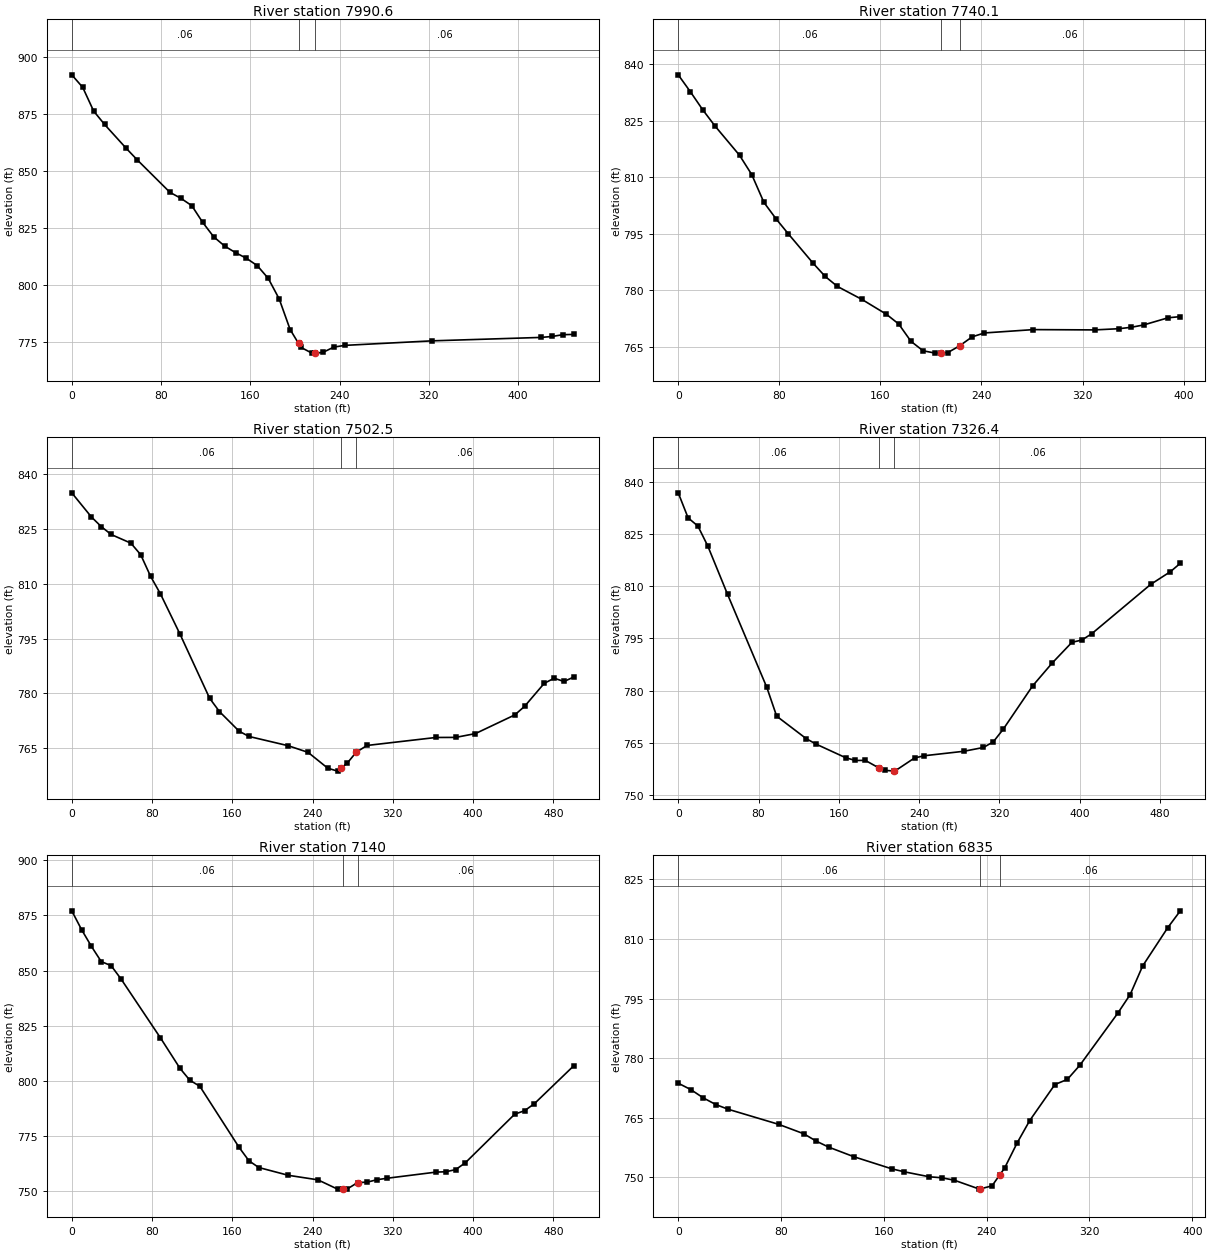
Type RM Length L Ch R = 1 ,7990.6  ,254.3,250.5,246.5
XS GIS Cut Line= 2
      1689301.89      325033.492     1688947.216      325310.505
#Sta/Elev= 30
       0   892.3     9.8  886.81    19.6   876.4    29.4  870.51    48.9  859.98
    58.7  854.95      88   840.7    97.8  838.09   107.6  834.84   117.4  827.47
   127.2  821.18     137  817.13   146.8  814.21   156.5  811.77   166.3   808.5
   176.1  802.93   185.9  793.91   195.7  780.48   203.3774.3373   205.4  772.64
   215.2  770.11   218.3770.2009     225   770.4   234.8  772.75   244.6  773.51
   322.8   775.5   420.7  777.01   430.5  777.42   440.2  778.21     450  778.33
#Mann= 3 , 0 , 0
       0     .06       0   203.3    .045       0   218.3     .06       0
Bank Sta=203.3,218.3
XS Rating Curve= 0 ,0
Exp/Cntr=0.3,0.1

Type RM Length L Ch R = 1 ,7740.1  ,227.4,237.6,247.9
XS GIS Cut Line= 2
     1689044.541      324926.316     1688780.129      325222.977
#Sta/Elev= 30
       0  837.19     9.7  832.65    19.4  827.89    29.1  823.59    48.5  815.82
    58.2  810.67    67.8   803.3    77.5  798.89    87.2  794.91   106.6  787.19
   116.3  783.62     126  780.96   145.4  777.51   164.8  773.56   174.5  770.98
   184.2  766.38   193.8  763.86   203.5  763.24   207.7  763.29   213.2  763.35
   222.7  765.18   232.6  767.56   242.3   768.6   281.1  769.49   329.6  769.41
   348.9  769.73   358.6  770.11   368.3  770.72   387.7  772.63   397.4  772.94
#Mann= 3 , 0 , 0
       0     .06       0   207.7    .045       0   222.7     .06       0
Bank Sta=207.7,222.7
XS Rating Curve= 0 ,0
Exp/Cntr=0.3,0.1

Type RM Length L Ch R = 1 ,7502.5  ,187.2,175.8,164.3
XS GIS Cut Line= 2
     1689048.364      324778.807     1688585.267      324968.314
#Sta/Elev= 30
       0  834.95    19.6  828.32    29.4  825.69    39.2  823.53    58.9  821.15
    68.7  817.98    78.5  812.08    88.3  807.28   107.9  796.18   137.4  778.61
   147.2  774.96   166.8  769.58   176.6  768.14   215.8  765.59   235.5  763.78
   255.1  759.44   264.9  758.63   268.5  759.45   274.7  760.87   283.5  763.82
   294.3  765.67     363  767.86   382.6  767.88   402.3  768.92   441.5  774.04
   451.3  776.39   470.9  782.71   480.8  784.11   490.6  783.21   500.4  784.45
#Mann= 3 , 0 , 0
       0     .06       0   268.5    .045       0   283.5     .06       0
Bank Sta=268.5,283.5
XS Rating Curve= 0 ,0
Exp/Cntr=0.3,0.1

Type RM Length L Ch R = 1 ,7326.4  ,193.3,186.3,179.4
XS GIS Cut Line= 2
     1688841.264      324578.354      1688522.33       324963.91
#Sta/Elev= 30
       0  836.77     9.8   829.6    19.6  827.23    29.4  821.54    49.1  807.67
    88.3  780.93    98.1  772.68   127.6  766.22   137.4  764.66   166.8  760.77
   176.6  759.96   186.4     760   200.4  757.76     206  757.14   215.4  756.92
   215.8  756.91   235.5  760.69   245.3  761.33   284.5   762.6   304.2   763.7
     314  765.31   323.8  768.89   353.2  781.37   372.8  787.96   392.4  793.88
   402.3  794.53   412.1  796.33   470.9   810.5   490.6  814.16   500.4  816.55
#Mann= 3 , 0 , 0
       0     .06       0   200.4    .045       0   215.4     .06       0
Bank Sta=200.4,215.4
XS Rating Curve= 0 ,0
Exp/Cntr=0.3,0.1

Type RM Length L Ch R = 1 ,7140    ,296.3,304.9,313.5
XS GIS Cut Line= 2
     1688659.095      324380.854     1688471.708      324844.814
#Sta/Elev= 30
       0  877.02     9.8  868.48    19.6  860.92    29.4  854.03    39.2  852.21
    49.1  846.17    88.3  819.57   107.9  805.69   117.7  800.31   127.6  797.62
   166.8  769.92   176.6  763.86   186.4  760.82   215.8   757.3   245.3  755.25
   264.9  751.04   269.9   751.1   274.7  751.16   284.9  754.01   294.3  754.19
   304.2   755.3     314  755.95     363  758.74   372.8  758.91   382.6  759.86
   392.4  763.03   441.5  784.98   451.3  786.54   461.1  789.73   500.4  806.92
#Mann= 3 , 0 , 0
       0     .06       0   269.9    .045       0   284.9     .06       0
Bank Sta=269.9,284.9
XS Rating Curve= 0 ,0
Exp/Cntr=0.3,0.1

Type RM Length L Ch R = 1 ,6835    ,182.2,183.8,185.5
XS GIS Cut Line= 2
     1688449.867      324398.064     1688196.326       324695.38
#Sta/Elev= 30
       0  773.66     9.8  772.05    19.5  769.96    29.3  768.27    39.1  767.07
    78.2  763.29    97.7  760.92   107.4  759.06   117.2  757.54   136.8  755.12
   166.1  752.09   175.8  751.34   195.4  750.08   205.1  749.83   214.9  749.21
   234.4  746.97   235.2  747.04   244.2   747.8   250.2  750.56     254   752.3
   263.8  758.66   273.5  764.24   293.1  773.33   302.8  774.62   312.6  778.22
   341.9  791.24   351.7  796.01   361.4  803.21     381  812.89   390.7   817.1
#Mann= 3 , 0 , 0
       0     .06       0   235.2    .045       0   250.2     .06       0
Bank Sta=235.2,250.2
XS Rating Curve= 0 ,0
Exp/Cntr=0.3,0.1

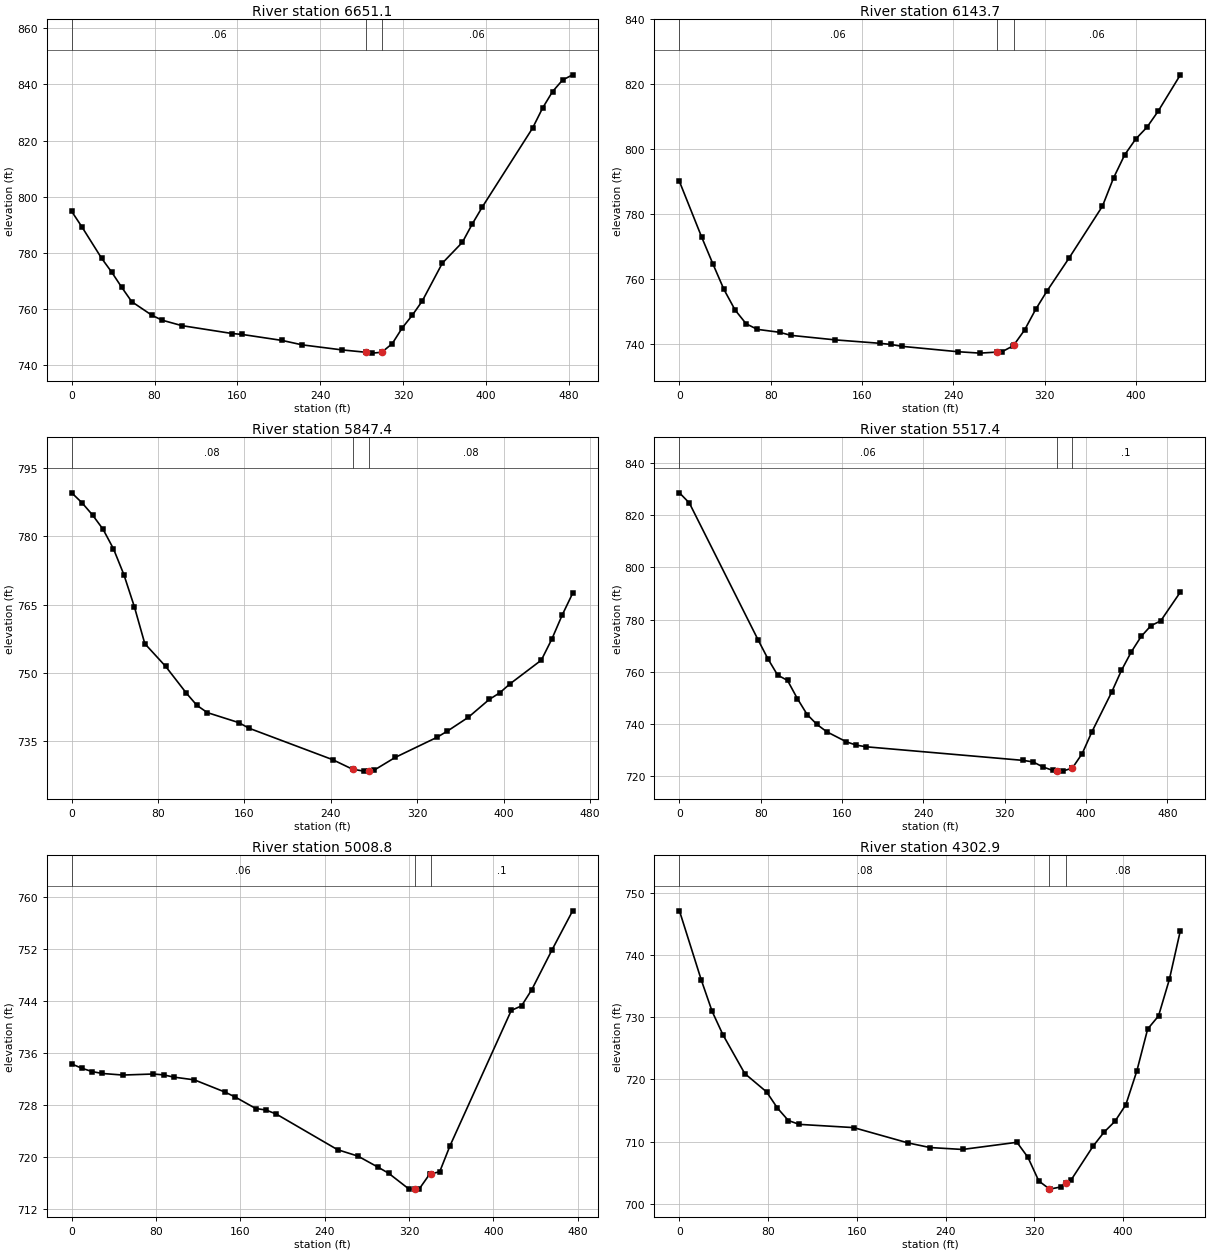
Type RM Length L Ch R = 1 ,6651.1  ,497.4,507.2,517.1
XS GIS Cut Line= 2
     1688347.322      324270.403     1688006.971      324614.203
#Sta/Elev= 30
       0  794.74     9.7  789.33      29     778    38.7  773.08    48.4  767.66
      58   762.6    77.4  757.78    87.1  756.04   106.4  754.07   154.8  751.27
   164.5  750.94   203.2   748.8   222.5  747.23   261.2  745.42   284.4  744.58
   290.3  744.28   299.4  744.58   309.6  747.66   319.3   753.3     329   757.8
   338.6  762.87     358  776.35   377.3  783.74     387  790.36   396.7  796.41
   445.1  824.41   454.8  831.57   464.4  837.43   474.1  841.55   483.8   843.4
#Mann= 3 , 0 , 0
       0     .06       0   284.4    .045       0   299.4     .06       0
Bank Sta=284.4,299.4
XS Rating Curve= 0 ,0
Exp/Cntr=0.3,0.1

Type RM Length L Ch R = 1 ,6143.7  ,297.2,296.2,291.9
XS GIS Cut Line= 2
     1688135.746      323962.131     1687726.818      324121.988
#Sta/Elev= 30
       0     790    19.5  772.85    29.3  764.63      39  756.74    48.8   750.4
    58.5  746.15    68.3  744.45    87.8  743.55    97.6  742.61   136.6  741.21
   175.6  740.16   185.4   739.8   195.1  739.22   243.9  737.57   263.4  737.13
   278.3  737.45     283   737.6   292.7  739.42   293.3  739.71   302.5  744.23
   312.2  750.57     322  756.16   341.5   766.4   370.8   782.4   380.5  791.08
   390.3  798.22     400   803.1   409.8  806.71   419.6  811.64   439.1  822.86
#Mann= 3 , 0 , 0
       0     .06       0   278.3    .045       0   293.3     .06       0
Bank Sta=278.3,293.3
XS Rating Curve= 0 ,0
Exp/Cntr=0.3,0.1

Type RM Length L Ch R = 1 ,5847.4  ,342.7,330.3,321.1
XS GIS Cut Line= 2
     1688076.114      323688.169     1687646.522      323863.578
#Sta/Elev= 30
       0  789.58     9.7  787.35    19.3   784.7      29  781.58    38.7  777.26
    48.3  771.61      58  764.56    67.7  756.42      87  751.42   106.3  745.51
     116  742.84   125.7  741.25   154.7  739.06   164.3  737.82   241.7  730.91
   260.2   728.8   270.7  728.39   275.2  728.51   280.4  728.64   299.7  731.41
   338.4  735.83     348  737.19   367.4  740.23   386.7  744.14   396.4  745.59
     406  747.58     435  752.79   444.7   757.4   454.4  762.74     464  767.48
#Mann= 3 , 0 , 0
       0     .08       0   260.2    .045       0   275.2     .08       0
Bank Sta=260.2,275.2
XS Rating Curve= 0 ,0
Exp/Cntr=0.3,0.1

Type RM Length L Ch R = 1 ,5517.4  ,516.9,508.1,499.4
XS GIS Cut Line= 2
     1687794.737      323317.182     1687511.116      323720.221
#Sta/Elev= 30
       0  828.65     9.7  824.76    77.3  772.23      87  764.93    96.6  758.65
   106.3  756.62     116  749.63   125.6  743.52   135.3   739.7     145  736.88
   164.3  733.02   173.9  731.77   183.6  731.13   338.2   725.9   347.9  725.32
   357.5   723.4   367.2  722.06     371  721.95   376.9  721.78     386  722.88
   386.5  722.94   396.2   728.5   405.9  736.98   425.2   752.1   434.8  760.45
   444.5  767.56   454.2  773.48   463.8  777.61   473.5   779.5   492.8  790.54
#Mann= 3 , 0 , 0
       0     .06       0     371    .045       0     386      .1       0
Bank Sta=371,386
XS Rating Curve= 0 ,0
Exp/Cntr=0.3,0.1

Type RM Length L Ch R = 1 ,5008.8  ,697,705.7,714.5
XS GIS Cut Line= 2
     1687194.536      323094.464     1687089.309      323557.947
#Sta/Elev= 30
       0  734.32     9.7  733.66    19.4  733.15    29.1  732.86    48.5  732.62
    77.6  732.78    87.3  732.64      97   732.3   116.4  731.88   145.5     730
   155.2  729.24   174.6  727.48   184.3  727.25     194  726.64   252.2  721.16
   271.6  720.17     291  718.44   300.7  717.54   320.1   715.1   325.6  715.12
   329.8  715.14   339.5  717.37   340.6  717.42   349.2  717.78   358.9  721.74
   417.1  742.55   426.8  743.24   436.5  745.72   455.9  751.89   475.3  757.84
#Mann= 3 , 0 , 0
       0     .06       0   325.6    .045       0   340.6      .1       0
Bank Sta=325.6,340.6
XS Rating Curve= 0 ,0
Exp/Cntr=0.3,0.1

Type RM Length L Ch R = 1 ,4302.9  ,567.6,559,550.4
XS GIS Cut Line= 2
     1686713.615       322792.37     1686453.767      323161.902
#Sta/Elev= 30
       0  747.07    19.6  736.01    29.5  730.91    39.3  727.14    58.9  720.94
    78.6  717.99    88.4  715.39    98.2   713.4     108  712.78   157.1  712.26
   206.2   709.8   225.9  709.06   255.3  708.75   304.4   709.9   314.3  707.49
   324.1  703.69   333.5  702.43   333.9  702.38   343.7  702.72   348.5  703.31
   353.5  703.92   373.2  709.31     383  711.53   392.8  713.27   402.6  715.93
   412.5  721.33   422.3  728.09   432.1  730.19   441.9  736.07   451.8   743.9
#Mann= 3 , 0 , 0
       0     .08       0   333.5    .045       0   348.5     .08       0
Bank Sta=333.5,348.5
XS Rating Curve= 0 ,0
Exp/Cntr=0.3,0.1

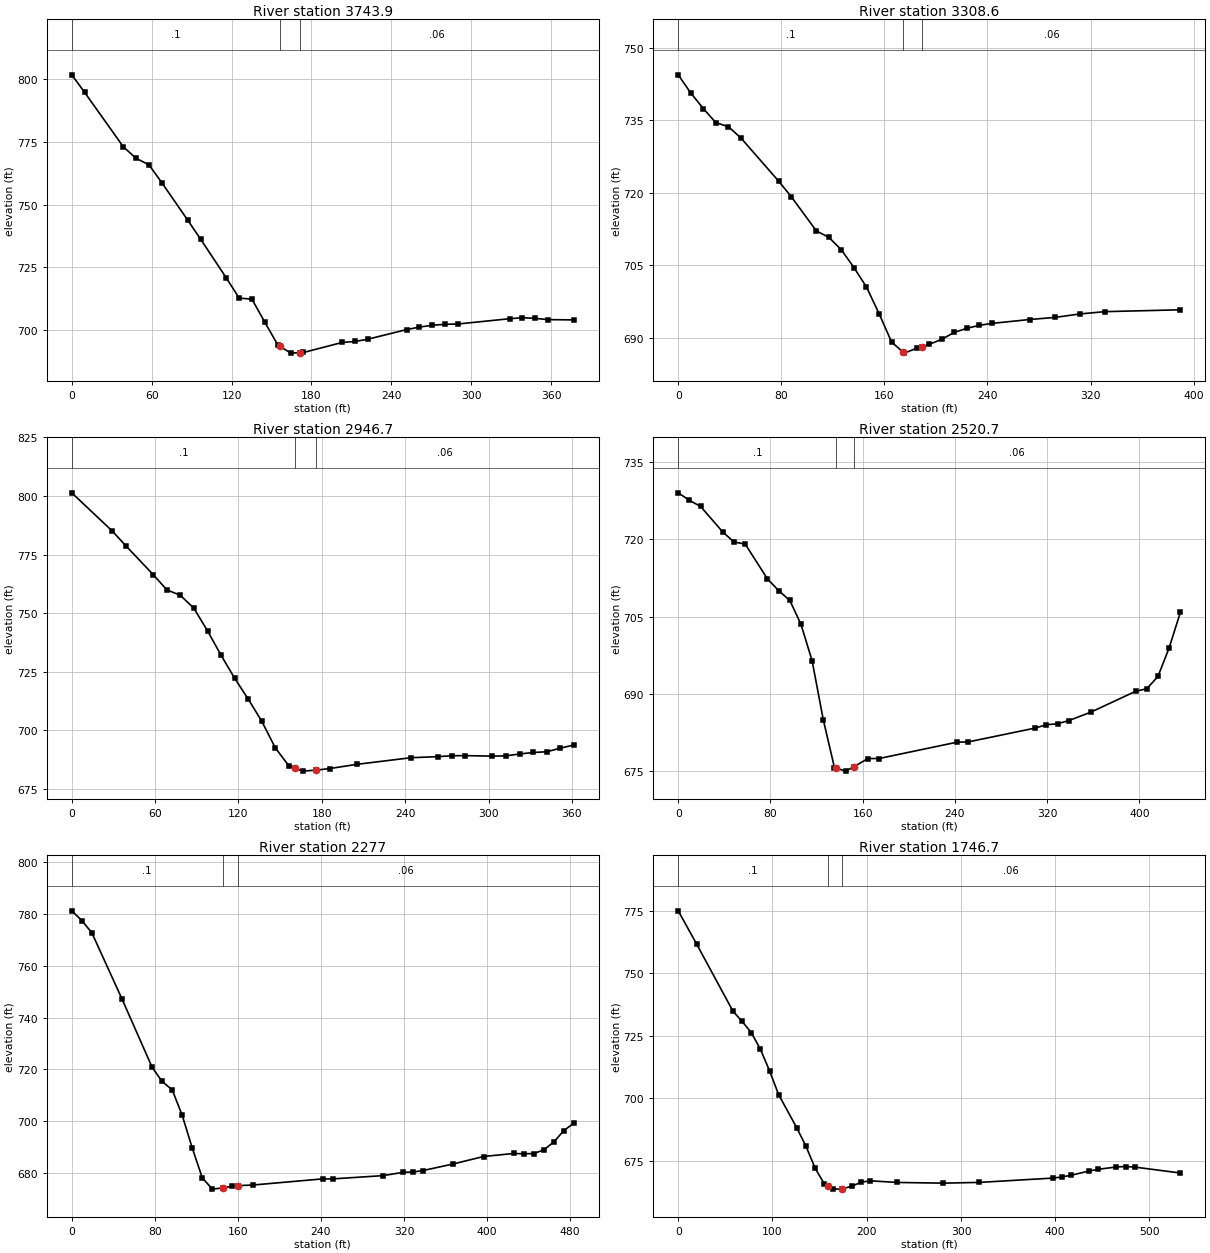
Type RM Length L Ch R = 1 ,3743.9  ,442.5,434.8,427.2
XS GIS Cut Line= 2
     1686181.119      322603.345     1686093.706        322970.1
#Sta/Elev= 30
       0  801.84     9.7   794.8    38.7   773.1    48.3  768.48      58  765.89
    67.7   758.7      87  743.84    96.7  736.24     116  720.75   125.7  712.68
   135.3  712.22     145  702.98   154.7  693.97   156.5  693.36   164.4  690.68
   171.5  690.87     174  690.94     203  694.94   212.7  695.33   222.4  696.25
   251.4  700.08     261  701.08   270.7  701.81   280.4   702.2     290  702.32
   328.7  704.42   338.4  704.83     348  704.56   357.7  704.06     377  703.95
#Mann= 3 , 0 , 0
       0      .1       0   156.5    .045       0   171.5     .06       0
Bank Sta=156.5,171.5
XS Rating Curve= 0 ,0
Exp/Cntr=0.3,0.1

Type RM Length L Ch R = 1 ,3308.6  ,348.2,361.8,375.4
XS GIS Cut Line= 2
     1685712.368      322497.895     1685754.492      322885.289
#Sta/Elev= 30
       0  744.45     9.7   740.7    19.5  737.45    29.2  734.56      39   733.7
    48.7  731.36    77.9  722.45    87.7  719.23   107.2  712.14   116.9   710.8
   126.6  708.23   136.4  704.54   146.1  700.52   155.9     695   165.6  689.13
   174.5  687.04   175.4  686.83   185.1  687.84   189.5   688.2   194.8  688.64
   204.6   689.7   214.3  691.14   224.1  691.97   233.8  692.59   243.6  692.99
   272.8  693.79   292.3  694.22   311.7  694.94   331.2  695.42   389.7   695.8
#Mann= 3 , 0 , 0
       0      .1       0   174.5    .045       0   189.5     .06       0
Bank Sta=174.5,189.5
XS Rating Curve= 0 ,0
Exp/Cntr=0.3,0.1

Type RM Length L Ch R = 1 ,2946.7  ,436.9,425.9,414.8
XS GIS Cut Line= 2
     1685464.809      322446.493     1685293.578      322764.777
#Sta/Elev= 30
       0  801.31    29.3  784.93    39.1  778.61    58.6  766.44    68.4  759.95
    78.1  757.63    87.9   752.1    97.7  742.46   107.4  732.11   117.2  722.29
     127  713.36   136.8  703.87   146.5  692.55   156.3  684.86   160.8  683.84
   166.1  682.63   175.8  683.05   185.6  683.72   205.1  685.52   244.2  688.35
   263.7  688.82   273.5  689.18   283.3  689.24   302.8  689.02   312.6  689.15
   322.4  689.95   332.1  690.58   341.9  690.89   351.6  692.42   361.4  693.77
#Mann= 3 , 0 , 0
       0      .1       0   160.8    .045       0   175.8     .06       0
Bank Sta=160.8,175.8
XS Rating Curve= 0 ,0
Exp/Cntr=0.3,0.1

Type RM Length L Ch R = 1 ,2520.7  ,241.3,243.7,246.2
XS GIS Cut Line= 2
     1684970.073      322393.949     1684968.277      322829.417
#Sta/Elev= 30
       0  729.01     9.7  727.55    19.4  726.37    38.7  721.39    48.4  719.47
    58.1  719.06    77.4  712.31    87.1  710.03    96.8  708.12   106.4  703.53
   116.1  696.45   125.8     685   135.5   675.7   137.1  675.59   145.2  675.01
   152.1  675.82   164.5  677.45   174.2  677.46   241.9  680.63   251.6  680.68
   309.7  683.37   319.4  684.02     329   684.2   338.7  684.81     358  686.46
   396.8  690.51   406.4  690.99   416.1  693.38   425.8  698.92   435.5  705.79
#Mann= 3 , 0 , 0
       0      .1       0   137.1    .045       0   152.1     .06       0
Bank Sta=137.1,152.1
XS Rating Curve= 0 ,0
Exp/Cntr=0.3,0.1

Type RM Length L Ch R = 1 ,2277    ,514.3,530.1,545.8
XS GIS Cut Line= 2
      1684743.18      322376.961     1684689.314      322857.451
#Sta/Elev= 30
       0  781.16     9.7  777.42    19.3  772.71    48.4  747.14    77.4  720.79
      87  715.34    96.7  712.13   106.4  702.22     116   689.7   125.7  678.14
   135.4  673.81   145.2  674.28   154.7  674.96   160.2  675.17   174.1  675.38
   241.8  677.77   251.4  677.76   299.8  679.02   319.1  680.29   328.8  680.42
   338.4  680.99   367.5  683.53   396.5  686.39   425.5  687.56   435.2  687.43
   444.8  687.53   454.5  688.92   464.2  691.98   473.8  696.38   483.5  699.24
#Mann= 3 , 0 , 0
       0      .1       0   145.2    .045       0   160.2     .06       0
Bank Sta=145.2,160.2
XS Rating Curve= 0 ,0
Exp/Cntr=0.3,0.1

Type RM Length L Ch R = 1 ,1746.7  ,385,398.1,411.1
XS GIS Cut Line= 2
     1684370.126      322230.103     1683982.192      322595.189
#Sta/Elev= 30
       0  774.93    19.4  761.72    58.1  734.78    67.8  730.71    77.5  726.22
    87.2  719.57    96.9  710.95   106.5  701.45   125.9  688.06   135.6  680.75
   145.3  671.97     155  665.75   158.6  664.97   164.7  663.65   173.6   663.7
     184  664.81   193.7  666.36   203.4  666.98   232.5  666.32   280.9  666.04
   319.6  666.34   397.1  668.06   406.8  668.48   416.5  669.17   435.8  670.89
   445.5  671.58   464.9  672.51   474.6  672.68   484.3  672.47   532.7   670.1
#Mann= 3 , 0 , 0
       0      .1       0   158.6    .045       0   173.6     .06       0
Bank Sta=158.6,173.6
XS Rating Curve= 0 ,0
Exp/Cntr=0.3,0.1

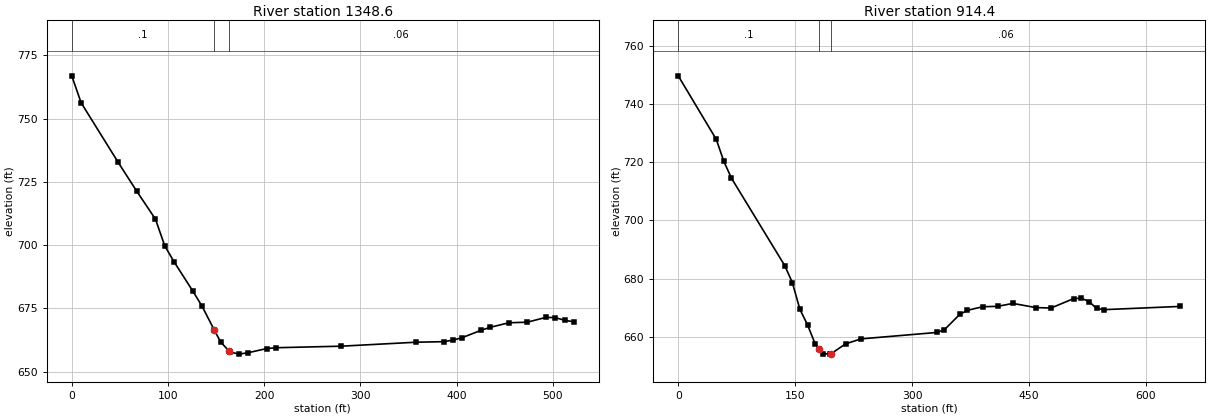
Type RM Length L Ch R = 1 ,1348.6  ,436.7,433.9,435.4
XS GIS Cut Line= 2
     1684262.182      321958.211     1683748.619      322050.185
#Sta/Elev= 30
       0  766.89     9.7  756.26    48.3  732.66    67.6  721.26      87  710.25
    96.6  699.74   106.3  693.42   125.6  681.98   135.3  675.94   147.9666.6205
   154.6  661.82   162.9658.3621   164.2  657.82   173.9  656.96   183.6  657.55
   202.9  659.18   212.6  659.49   280.2   660.1   357.5  661.66   386.5  661.88
   396.1  662.48   405.8  663.48   425.1  666.35   434.8  667.55   454.1  669.34
   473.4  669.58   492.8  671.49   502.4  671.36   512.1  670.35   521.7   669.7
#Mann= 3 , 0 , 0
       0      .1       0   147.9    .045       0   162.9     .06       0
Bank Sta=147.9,162.9
XS Rating Curve= 0 ,0
Exp/Cntr=0.3,0.1

Type RM Length L Ch R = 1 ,914.4   ,957.6,914.2,865.6
XS GIS Cut Line= 2
     1684264.803      321504.915     1683649.296      321694.304
#Sta/Elev= 30
       0  749.78    48.8   727.9    58.5  720.34    68.3  714.54   136.6  684.48
   146.4   678.6   156.1  669.39   165.9  664.05   175.6  657.55   180.8  655.77
   185.4   654.2   195.2  654.01   195.8  654.11   214.7  657.54   234.2  659.25
   331.8  661.47   341.5  662.44     361  667.65   370.8  669.08   390.3  670.31
   409.8  670.46   429.3  671.46   458.6  670.03   478.1  669.87   507.4  673.14
   517.1  673.23   526.9  672.11   536.6  669.72   546.4  669.32     644  670.43
#Mann= 3 , 0 , 0
       0      .1       0   180.8    .045       0   195.8     .06       0
Bank Sta=180.8,195.8
XS Rating Curve= 0 ,0
Exp/Cntr=0.3,0.1

Chan Stop Cuts=-1
Use User Specified Reach Order=0
Composite Channel Slope=5